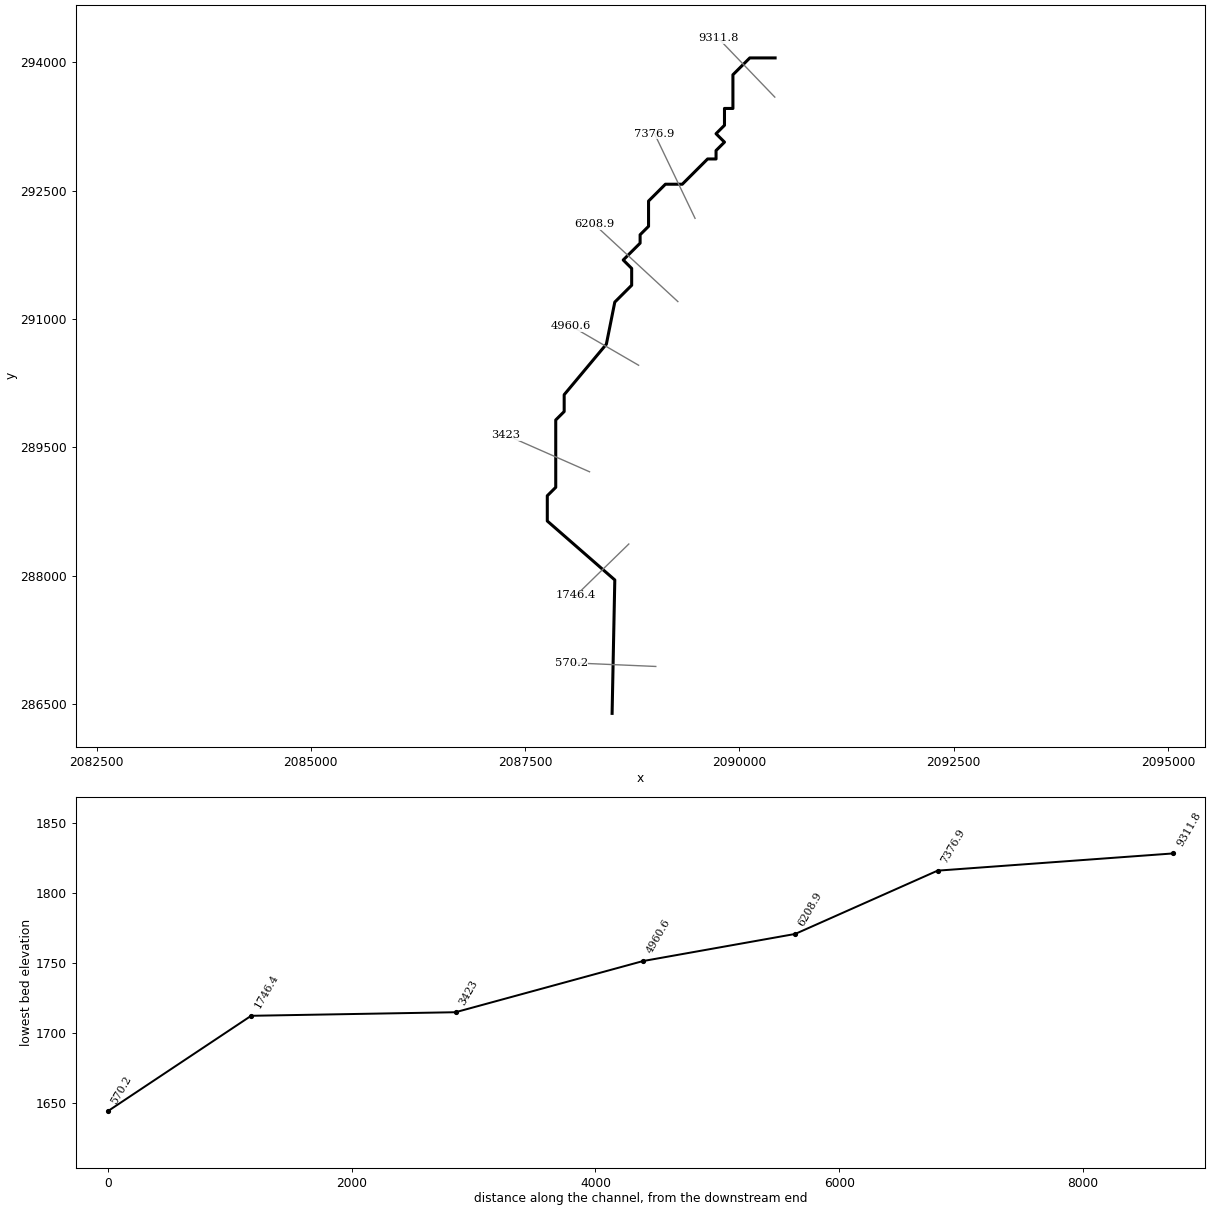
--- MillCkT2.prj (project) ---

Proj Title=MillCkT2
Current Plan=p01
Geom File=g01
Flow File=f01
Plan File=p01
DSS Export Rating Curves=0
DSS Export Rating Curve Sorted=0
DSS Export Volume Flow Curves=0
DXF OffsetX=0
DXF OffsetY=0
DXF ScaleX=0
DXF ScaleY=0

--- MillCkT2.p01 (plan) ---

Plan Title=Floodplain
Program Version=4.00
Geom File=g01
Flow File=f01
K Sum by GR=0
Std Step Tol=0.01
Critical Tol=0.01
Num of Std Step Trials=20
Max Error Tol=0.3
Flow Tol Ratio=0.001
Split Flow NTrial=30
Split Flow Tol=0.02
Split Flow Ratio=0.02
Log Output Level=0
Friction Slope Method=1
Unsteady Friction Slope Method=2
Unsteady Bridges Friction Slope Method=1
Global Log Level=0
CheckData=False
Run HTab=0
Run UNet=0
Run PostProcess=0
UNET Theta=0
UNET Theta Warmup=0
UNET ZTol=0
UNET ZSATol=0
UNET MxIter=0
UNET MaxInSteps=0
UNET DtIC=0
UNET DtMin=0
UNET MaxCRTS=0
UNET WFStab=0
UNET SFStab=0
UNET WFX=0
UNET SFX=0
UNET DSS MLevel=0
UNET DZMax Abort=0
UNET Convert EG Bridges=0
UNET Use Existing IB Tables=0
UNET Froude Limit=0
UNET Froude Power=0
Write IC File=0
Echo Input=False
Echo Output=False
Write Detailed=0

--- MillCkT2.f01 (steady flow) ---

Flow Title=Moglen and others (2006)
Program Version=4.00
Number of Profiles=1
Profile Names=P100yr
River Rch & RM=MillCkT2,Main      ,9311.8
529.4808
River Rch & RM=MillCkT2,Main      ,6208.9
576.2684
River Rch & RM=MillCkT2,Main      ,4960.6
637.8743
River Rch & RM=MillCkT2,Main      ,3423
690.3383
River Rch & RM=MillCkT2,Main      ,1746.4
764.4173
Boundary for River Rch & Prof#=MillCkT2,Main      ,1
Up Type=0
Dn Type=3
Dn Slope=0.026937

--- MillCkT2.g01 (geometry) ---

Geom Title=DNR 5-ft DEM
Program Version=4.00

River Reach=MillCkT2     ,Main
Reach XY= 30
     2090415.819      294050.317     2090120.547      294050.317
     2089923.699      293853.469     2089923.699      293459.773
     2089825.275      293459.773     2089825.275      293262.925
     2089726.851      293164.501     2089825.275      293066.077
     2089726.851      292967.653     2089726.851      292869.229
     2089628.427      292869.229     2089333.155      292573.957
     2089136.307      292573.957     2088939.459      292377.109
     2088939.459      292081.837     2088841.035      291983.413
     2088841.035      291884.989     2088644.187      291688.141
     2088742.611      291589.717     2088742.611      291392.869
     2088545.763      291196.021     2088447.339      290703.901
     2087955.219      290113.357     2087955.219      289916.509
     2087856.795      289818.085     2087856.795      289030.693
     2087758.371      288932.269     2087758.371      288636.997
     2088545.763      287948.029     2088514.313      286388.440

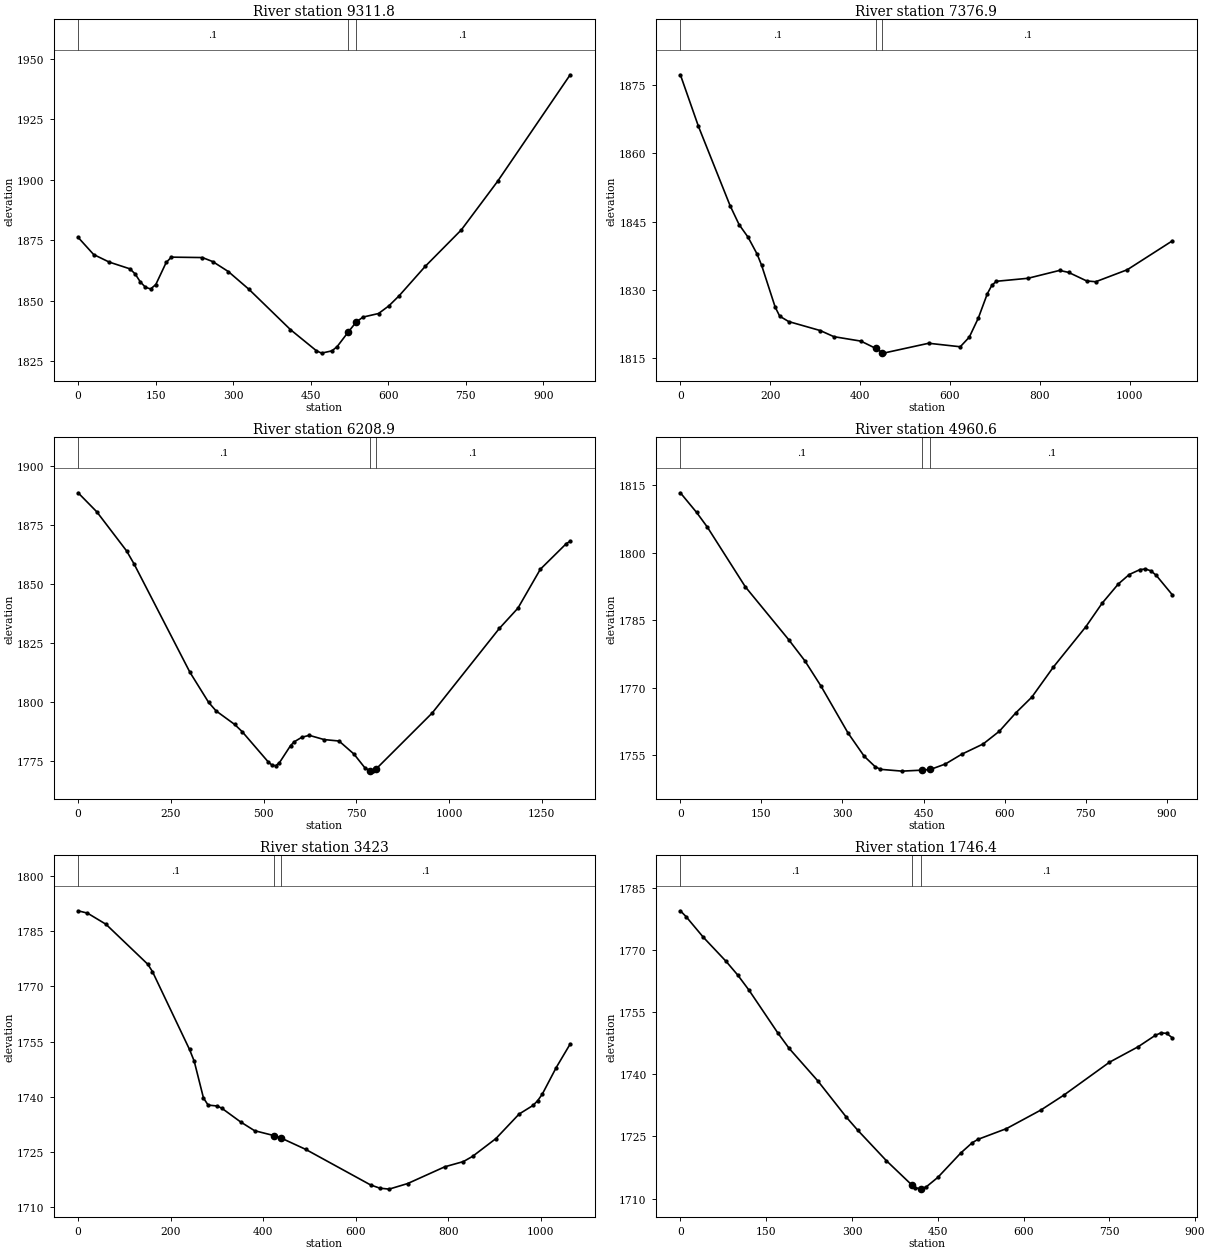
Type RM Length L Ch R = 1 ,9311.8,1932.4,1934.9,1908.1
XS GIS Cut Line= 2
     2090412.262      293592.259     2089753.878      294279.268
#Sta/Elev= 30
       0 1876.16    30.0 1869.09    60.1 1865.97   100.2 1863.18   110.2 1861.09
   120.2 1857.82   130.2 1855.57   140.2 1854.88   150.2 1856.70   170.3 1865.81
   180.3 1868.01   240.4 1867.84   260.4 1866.17   290.5 1862.06   330.5 1854.71
   410.7 1838.08   460.8 1829.38   470.8 1828.39   490.8 1829.32   500.8 1831.04
   522.8 1837.20   537.8 1841.22   550.9 1843.26   581.0 1844.74   601.0 1847.90
   621.0 1852.10   671.1 1864.16   741.2 1879.28   811.3 1899.31   951.6 1943.27
#Mann= 3 , 0 , 0
       0     0.1       0   522.8   0.045       0   537.8     0.1       0
Bank Sta=   522.8,   537.8
Exp/Cntr=0.3,0.1

Type RM Length L Ch R = 1 ,7376.9,1159.2,1168,1176.7
XS GIS Cut Line= 2
     2089481.937      292175.304     2089009.619      293162.879
#Sta/Elev= 30
       0 1877.27    40.2 1865.92   110.5 1848.51   130.6 1844.33   150.6 1841.55
   170.7 1837.84   180.8 1835.35   210.9 1826.18   221.0 1824.18   241.0 1823.00
   311.3 1821.02   341.5 1819.68   401.7 1818.70   434.4 1817.11   449.4 1816.18
   451.9 1816.06   552.4 1818.23   622.7 1817.46   642.8 1819.58   662.8 1823.75
   682.9 1829.12   693.0 1830.98   703.0 1831.86   773.3 1832.52   843.6 1834.25
   863.7 1833.82   903.9 1831.94   924.0 1831.76   994.3 1834.40  1094.7 1840.76
#Mann= 3 , 0 , 0
       0     0.1       0   434.4   0.045       0   449.4     0.1       0
Bank Sta=   434.4,   449.4
Exp/Cntr=0.3,0.1

Type RM Length L Ch R = 1 ,6208.9,1235.5,1248.3,1255.3
XS GIS Cut Line= 2
     2089281.560      291202.041     2088308.297      292103.740
#Sta/Elev= 30
       0 1888.49    50.3 1880.46   130.7 1863.92   150.8 1858.42   301.5 1812.59
   351.8 1799.89   371.9 1796.28   422.2 1790.53   442.2 1787.52   512.6 1774.70
   522.7 1773.35   532.7 1773.08   542.8 1774.36   572.9 1781.61   583.0 1783.23
   603.1 1785.11   623.2 1785.94   663.4 1784.14   703.6 1783.53   743.8 1778.02
   774.0 1772.06   787.5 1770.95   794.0 1770.80   802.5 1771.55   954.9 1795.40
  1135.8 1831.13  1186.0 1839.72  1246.4 1856.17  1316.7 1867.05  1326.8 1867.97
#Mann= 3 , 0 , 0
       0     0.1       0   787.5   0.045       0   802.5     0.1       0
Bank Sta=   787.5,   802.5
Exp/Cntr=0.3,0.1

Type RM Length L Ch R = 1 ,4960.6,1534.9,1537.7,1540.4
XS GIS Cut Line= 2
     2088823.554      290457.782     2088036.356      290915.788
#Sta/Elev= 30
       0 1813.35    30.0 1808.99    50.0 1805.70   120.1 1792.45   200.2 1780.71
   230.2 1776.00   260.2 1770.35   310.2 1759.92   340.3 1754.72   360.3 1752.43
   370.3 1751.82   410.3 1751.42   447.7 1751.64   462.7 1751.79   490.4 1753.00
   520.4 1755.16   560.5 1757.47   590.5 1760.31   620.5 1764.34   650.5 1767.89
   690.6 1774.61   750.6 1783.57   780.6 1788.78   810.7 1793.08   830.7 1795.16
   850.7 1796.27   860.7 1796.40   870.7 1796.00   880.7 1795.00   910.7 1790.63
#Mann= 3 , 0 , 0
       0     0.1       0   447.7   0.045       0   462.7     0.1       0
Bank Sta=   447.7,   462.7
Exp/Cntr=0.3,0.1

Type RM Length L Ch R = 1 ,3423,1648.3,1676.6,1704.9
XS GIS Cut Line= 2
     2088251.047      289212.578     2087277.784      289641.959
#Sta/Elev= 30
       0 1790.59    20.1 1789.97    60.2 1786.93   150.5 1776.06   160.6 1774.07
   240.8 1752.86   250.9 1749.69   271.0 1739.64   281.0 1737.72   301.1 1737.46
   311.1 1736.82   351.2 1733.14   381.4 1730.75   423.4 1729.41   438.4 1728.77
   491.7 1725.68   632.2 1715.99   652.3 1715.10   672.4 1714.84   712.5 1716.36
   792.8 1720.92   833.0 1722.34   853.0 1723.77   903.2 1728.59   953.4 1735.27
   983.5 1737.62   993.5 1738.90  1003.6 1740.70  1033.7 1747.93  1063.8 1754.33
#Mann= 3 , 0 , 0
       0     0.1       0   423.4   0.045       0   438.4     0.1       0
Bank Sta=   423.4,   438.4
Exp/Cntr=0.3,0.1

Type RM Length L Ch R = 1 ,1746.4,1195.6,1176.2,1156.7
XS GIS Cut Line= 2
     2088709.052      288368.130     2088093.607      287766.998
#Sta/Elev= 30
       0 1779.43    10.0 1778.02    40.0 1773.07    80.0 1767.22   100.0 1763.98
   120.0 1760.28   170.1 1750.02   190.1 1746.25   240.1 1738.43   290.1 1729.66
   310.1 1726.50   360.1 1719.16     405 1713.25   410.2 1712.68     420 1712.30
   420.2 1712.29   430.2 1712.87   450.2 1715.13   490.2 1721.00   510.2 1723.47
   520.2 1724.29   570.2 1726.89   630.2 1731.36   670.2 1734.94   750.3 1742.91
   800.3 1746.63   830.3 1749.38   840.3 1749.99   850.3 1749.87   860.3 1748.77
#Mann= 3 , 0 , 0
       0     0.1       0     405   0.045       0     420     0.1       0
Bank Sta=     405,     420
Exp/Cntr=0.3,0.1

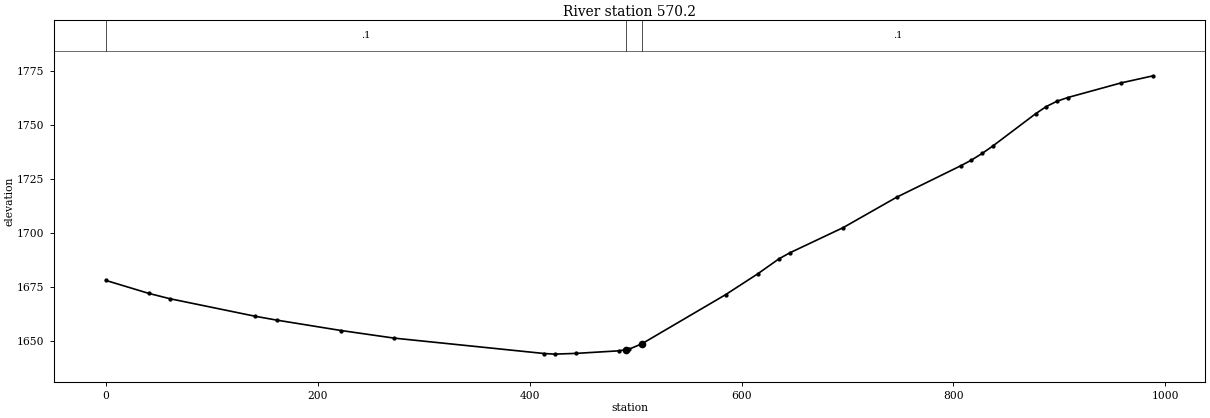
Type RM Length L Ch R = 1 ,570.2,569.7,570.2,570.7
XS GIS Cut Line= 2
     2089023.931      286936.862     2088036.356      286979.800
#Sta/Elev= 30
       0 1678.18    40.4 1672.19    60.5 1669.70   141.2 1661.56   161.4 1659.79
   221.9 1654.99   272.3 1651.45   413.6 1644.34   423.6 1644.05   443.8 1644.39
   484.2 1645.58   491.1 1646.14   494.2 1646.40   506.1 1648.88   585.0 1671.59
   615.3 1681.23   635.5 1688.22   645.6 1690.96   696.0 1702.64   746.4 1716.70
   807.0 1731.29   817.0 1733.89   827.1 1736.97   837.2 1740.41   877.6 1755.36
   887.6 1758.68   897.7 1761.14   907.8 1762.85   958.2 1769.64   988.5 1772.93
#Mann= 3 , 0 , 0
       0     0.1       0   491.1   0.045       0   506.1     0.1       0
Bank Sta=   491.1,   506.1
Exp/Cntr=0.3,0.1